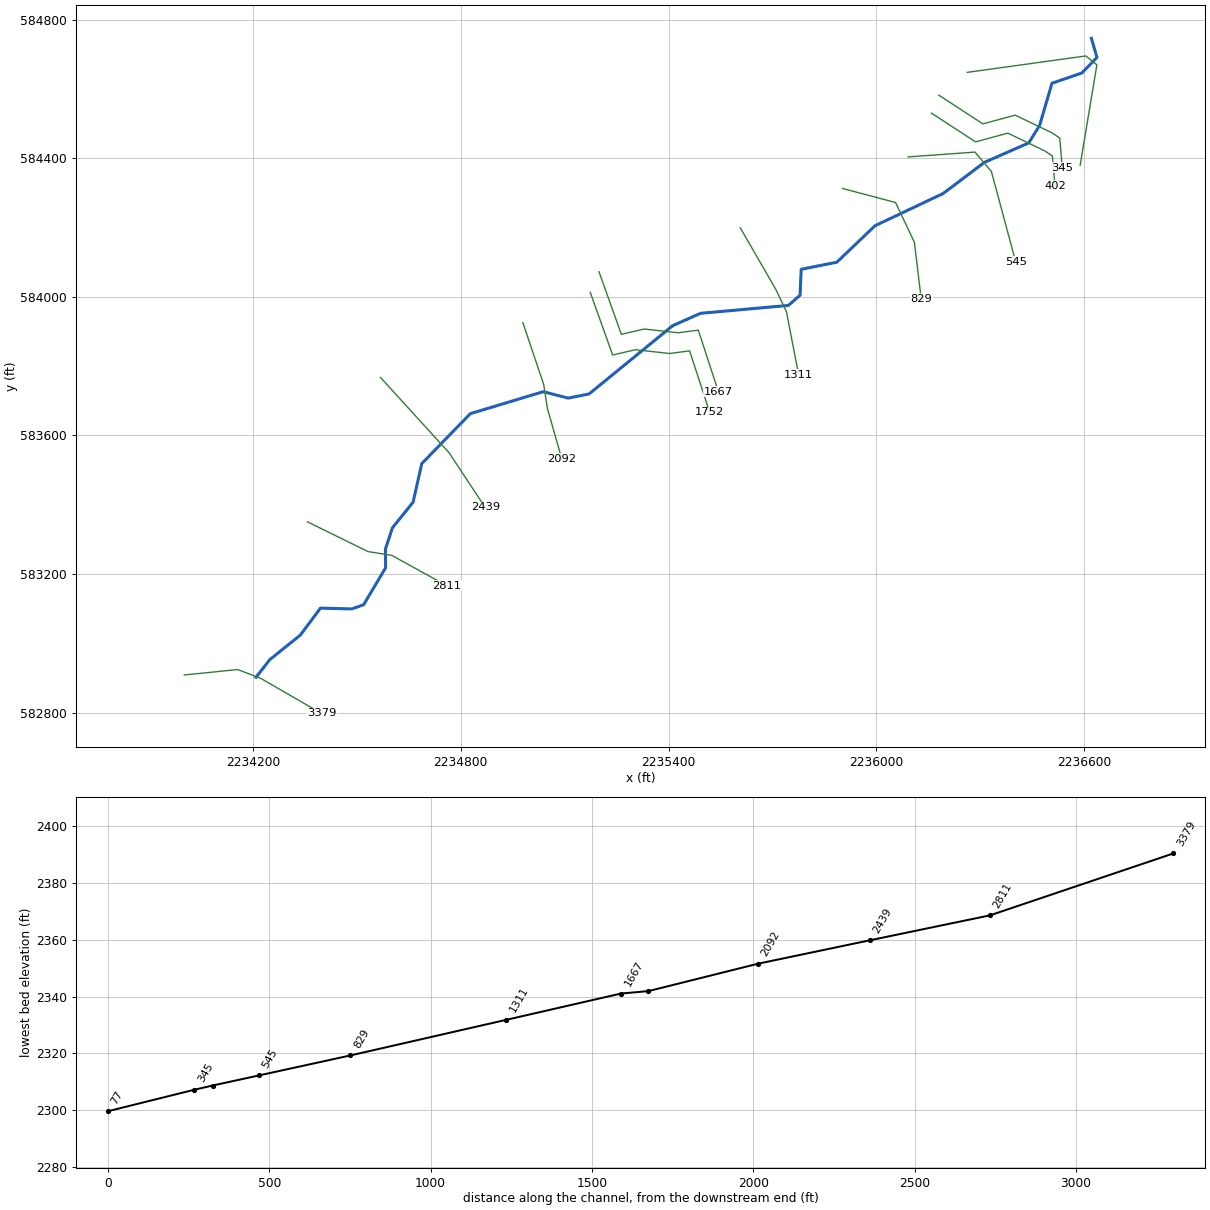
--- LIMEKNRN1.prj (project) ---

Proj Title=LIMEKNRN1
Current Plan=p01
Default Exp/Contr=0,0
English Units
Geom File=g01
Flow File=f01
Plan File=p01
BEGIN DESCRIPTION:
----------MODEL BY WOOD PLC 2022----------
AFH study
Randolph County, WV
HEC-RAS Version: RAS 6.2
Vertical Datum: NAVD88
Projection: NAD 1983 StatePlane West Virginia S FIPS 4702 (US Feet)
Terrain: 1-meter LIDAR (FEMA Region III 3DEP collected 2016-2018)
Land Use: 2019 NLCD
Hydrologic Method:
WV SIR2010-5033 regression equations
Additional Model Notes:
None
END DESCRIPTION:
DSS Export Rating Curves= 0
DSS Export Rating Curve Sorted= 0
DSS Export Volume Flow Curves= 0
DXF OffsetX= 0
DXF OffsetY= 0
DXF ScaleX= 0
DXF ScaleY= 0

--- LIMEKNRN1.p01 (plan) ---

Plan Title=Floodplain
Program Version=6.20
Short Identifier=Floodplain
Geom File=g01
Flow File=f01
Subcritical Flow
K Sum by GR= 0
Std Step Tol= 0.01
Critical Tol= 0.01
Num of Std Step Trials= 20
Max Error Tol= 0.3
Flow Tol Ratio= 0.001
Split Flow NTrial= 30
Split Flow Tol= 0.02
Split Flow Ratio= 0.02
Log Output Level= 0
Friction Slope Method= 1
Unsteady Friction Slope Method= 2
Unsteady Bridges Friction Slope Method= 1
Parabolic Critical Depth
Global Vel Dist= 0 , 0 , 0
Global Log Level= 0
CheckData=True
Encroach Param=-1 ,0,0, 0
Mapping Interval=1HOUR
Computation Time Step Use Courant=        0
Computation Time Step Use Time Series=    0
Computation Time Step Count To Double=0
Computation Time Step Max Doubling=0
Computation Time Step Max Halving=0
Computation Time Step Residence Courant=0
Run HTab= 0
Run UNet= 0
Run Sediment= 0
Run PostProcess= 0
Run WQNet= 0
Run RASMapper=-1
UNET Theta= 0
UNET Theta Warmup= 0
UNET ZTol= 0
UNET ZSATol= 0
UNET MxIter= 0
UNET Max Iter WO Improvement= 0
UNET MaxInSteps= 0
UNET DtIC= 0
UNET DtMin= 0
UNET MaxCRTS= 0
UNET WFStab= 0
UNET SFStab= 0
UNET WFX= 1
UNET SFX= 1
UNET Gravity=32.174
UNET 1D Methodology=Finite Difference
UNET DSS MLevel= 1
UNET Pardiso=0
UNET DZMax Abort= 0
UNET Use Existing IB Tables= 0
UNET Froude Reduction=False
UNET Froude Limit= 0
UNET Froude Power= 0
UNET D1 Cores= 0
UNET WindReference=Eulerian
UNET WindDragFormulation=Hsu (1988)
UNET D2 Coriolis=0
UNET D2 Cores= 0
UNET D2 Theta= 1
UNET D2 Theta Warmup= 1
UNET D2 Z Tol= 0.01
UNET D2 Volume Tol= 0.01
UNET D2 Max Iterations= 20
UNET D2 Equation= 0
UNET D2 RampUpFraction=0.1
UNET D2 TimeSlices= 1
UNET D2 Turbulence Formulation=Non-Conservative (original)
UNET D2 Eddy Viscosity=0.3
UNET D2 Transverse Eddy Viscosity=0.1
UNET D2 Smagorinsky Mixing=0
UNET D2 BCVolumeCheck=0
UNET D2 Cores=0
UNET D2 SolverType=PARDISO (Direct)
UNET D2 Minimum Iterations= 2147483647
UNET D2 Maximum Iterations= 2147483647
UNET D2 Restart Number= 10
UNET D2 Relaxation Coeff=1.3
UNET D2 SOR Precondition Iterations= 10
UNET D2 ILUT Maximum Fill= 8
UNET D2 ILUT Tolerance=1E-08
UNET D1D2 MaxIter= 0
UNET D1D2 ZTol=0.01
UNET D1D2 QTol=0.1
UNET D1D2 MinQTol=1
Write IC File= 0
Write IC File at Fixed DateTime=0
Write IC File at Sim End=0
Echo Input=False
Echo Parameters=False
Echo Output=False
Write Detailed= 0
HDF Write Warmup=0
HDF Write Time Slices=0
HDF Flush=0
HDF Compression= 1
HDF Chunk Size= 1
HDF Spatial Parts= 1
HDF Use Max Rows=0
HDF Fixed Rows= 1
Calibration Method= 0
Calibration Iterations= 20
Calibration Max Change=0.05
Calibration Tolerance=0.2
Calibration Maximum=1.5
Calibration Minimum=0.5
Calibration Optimization Method= 1
WQ AD Non Conservative
WQ ULTIMATE=-1
WQ Max Comp Step=1HOUR
WQ Output Interval=15MIN
WQ Output Selected Increments= 0
WQ Output face flow=0
WQ Output face velocity=0
WQ Output face area=0
WQ Output face dispersion=0
WQ Output cell volume=0
WQ Output cell surface area=0
WQ Output cell continuity=0
WQ Output cumulative cell continuity=0
WQ Output face conc=0
WQ Output face dconc_dx=0
WQ Output face courant=0
WQ Output face peclet=0
WQ Output face adv mass=0
WQ Output face disp mass=0
WQ Output cell mass=0
WQ Output cell source sink temp=0
WQ Output nsm pathways=0
WQ Output nsm derived pathways=0
WQ Create Restart=0
WQ Fixed Restart=0
WQ System Summary=0
WQ Write To DSS=0
Sorting and Armoring Iterations= 10
XS Update Threshold= 0.02
Bed Roughness Predictor= 0
Hydraulics Update Threshold= 0.02
Energy Slope Method= 1
Volume Change Method= 1
Sediment Retention Method= 0
Sediment TS Multiplier= 1
Warm Up Method= 0
XS Weighting Method= 0
Number of US Weighted Cross Sections= 1
Number of DS Weighted Cross Sections= 1
Upstream XS Weight=0
Main XS Weight=1
Downstream XS Weight=0
Number of DS XS's Weighted with US Boundary= 1
Upstream Boundary Weight= 1
Weight of XSs Associated with US Boundary= 0
Number of US XS's Weighted with DS Boundary= 1
Downstream Boundary Weight= 0.5
Weight of XSs Associated with DS Boundary= 0.5
Percentile Method= 0
Sediment Output Level= 3
Mass or Volume Output= 0
Output Increment Type= 1
Profile and TS Output Increment= 1
Transport Output Increment 1
XS Output Flag= 0
XS Output Increment= 10
Read HDF5 Sediment Hotstart= 0
Sediment Hotstart Type= 0
Write Gradation File= 0
Read Gradation Hotstart= 0
Write HDF5 File= 1
Write Binary Output= 1
Write DSS Sediment File= 0
DSS Sediment Output Type= 1
SV Curve= 0
Specific Gage Flag= 0
Subcell Erosion Methods= 0
Subcell Deposition Methods= 0
Advection Scheme= 1
Matrix Solver= 0
Implicit Weighting Factor= 1
Maximum Outer Loop Convergence Iterations= 5
Convergence Maximum Absolute= 0.001
Convergence RMSE= 0.0001
Grain Fractions Max Abs Error= 0.001
Max Subgrid Regions= 1
Max Subgrid Length Scale= 3.402823E+38
Initial Layer Thickness= 3.402823E+38
Min Layer Thickness= 3.402823E+38
Max Layer Thickness= 3.402823E+38
Number of Layers= 5

--- LIMEKNRN1.f01 (steady flow) ---

Flow Title=Flow
Program Version=6.20
Number of Profiles= 1
Profile Names=P100yr
River Rch & RM=LIMEKNRN1,Main,3379
     528
Boundary for River Rch & Prof#=LIMEKNRN1,Main            , 1
Up Type= 0
Dn Type= 3
Dn Slope=0.02888
DSS Import GetInterval= 0
DSS Import GetPeak= 0
DSS Import FillOption= 0

--- LIMEKNRN1.g01 (geometry) ---

Geom Title=Geometry
Program Version=6.20

River Reach=LIMEKNRN1       ,Main
Reach XY= 30
     2234209.014582901.9320000112234248.59699999582952.626000017
2234336.79100002583023.4599999932234395.02500004583101.546000004
2234485.40300001583099.1540000142234519.73800004583111.337000012
2234583.19453141583218.1090499612234582.60200003       583271.75
2234602.73100002583333.2169999932234662.48600002583407.487000003
2234687.52800003583518.7750000062234827.95500004583663.052000001
2235038.22027171 583726.383709522235110.22792885583707.900305584
2235170.64600003583719.9009999932235412.05199999583917.036000013
     2235492.521      583952.7132235746.03400004583975.452000007
2235779.74000002584004.9969999942235783.01665372584079.835495889
2235885.90158686584100.2120554892235996.14500003584205.511000007
2236192.39300004584298.3390000022236312.17000002584388.510000005
2236440.23900001      584444.8312236471.48899999584495.556999996
     2236507.066584616.9510000052236593.31348629584646.523261637
2236636.98986389584691.5401319862236620.83999226584746.585934609

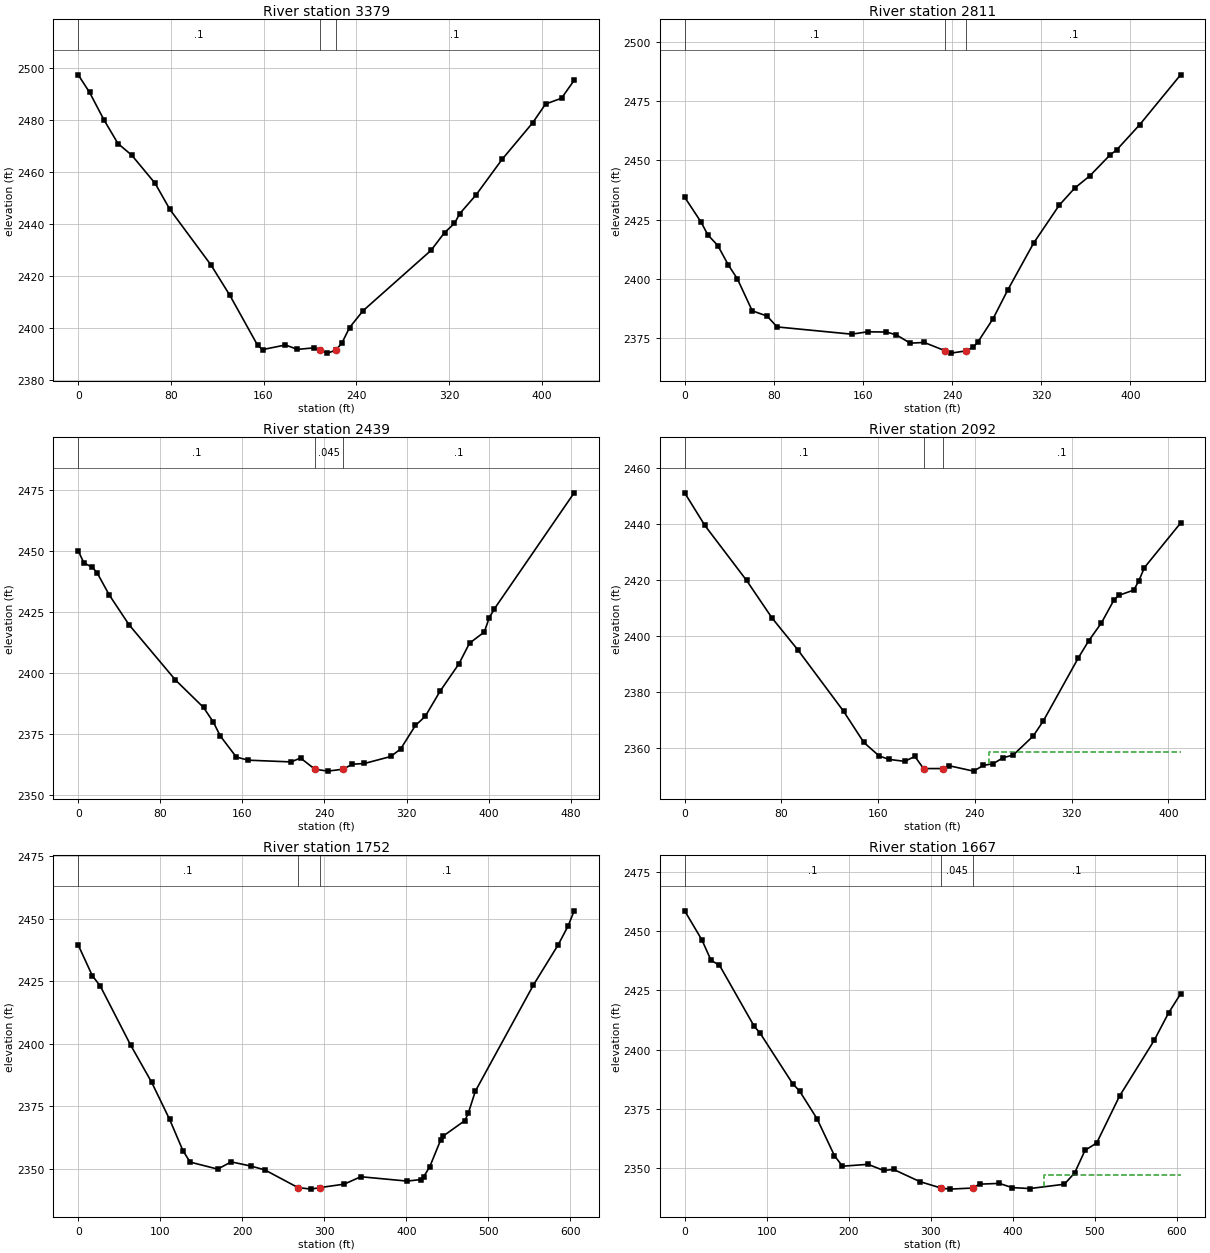
Type RM Length L Ch R = 1 ,3379    ,561.5,568.3,567.5
XS GIS Cut Line= 4
2234002.08959303582908.5358909082234156.13184732582924.202351932
2234223.80061195582898.1759039962234397.52800618582797.652645659
#Sta/Elev= 30
       0  2497.5     9.8 2490.74    22.2 2480.18    34.3 2471.06    46.3 2466.53
    66.4 2455.73    79.1 2445.72   114.7 2424.26   130.8 2412.72   154.8 2393.46
   159.2 2391.76   178.9 2393.54   189.2 2391.84   203.6 2392.43  208.612391.494
   214.9  2390.4   222.42391.496   227.8 2394.44   234.2 2400.22   245.9 2406.72
   304.5 2429.92   316.2 2436.77   324.8 2440.34   329.4 2444.11   343.3 2451.22
   365.9 2464.97   392.3 2479.05   403.4 2486.25   417.2  2488.5   428.1 2495.39
#Mann= 3 ,-1,0
       0      .1       0  208.61    .045       0   222.4      .1       0
Bank Sta=208.61,222.4
XS Rating Curve= 0 ,0
Exp/Cntr(USF)=0,0
Exp/Cntr=0.3,0.1

Type RM Length L Ch R = 1 ,2811    ,381.2,371.6,365.5
XS GIS Cut Line= 4
2234357.74901996583350.5069975042234532.28978271583264.805914198
2234600.60920854583253.9615608912234759.58310553583166.497628205
#Sta/Elev= 30
       0 2434.46    14.8 2423.89    20.7  2418.6    29.7 2414.06    39.3 2405.75
    47.3 2399.99    60.6 2386.48      74 2384.25    82.9 2379.67   149.8 2376.61
   164.2  2377.6   180.9 2377.52   189.9 2376.33   202.4 2372.81     215 2373.11
  234.082369.532   238.9  2368.6  252.392369.533   259.1 2371.16   263.2 2373.33
   276.8 2383.16   290.1  2395.4   313.3 2415.18   336.2 2431.12   349.9 2438.25
   363.6 2443.49   381.8 2452.34   387.6 2454.39   408.2 2465.01   445.1 2486.17
#Mann= 3 ,-1,0
       0      .1       0  234.08    .045       0  252.39      .1       0
Bank Sta=234.08,252.39
XS Rating Curve= 0 ,0
Exp/Cntr(USF)=0,0
Exp/Cntr=0.3,0.1

Type RM Length L Ch R = 1 ,2439    ,356.4,347.4,343.1
XS GIS Cut Line= 3
2234568.38095011583767.4804279642234766.09696881583550.540044882
2234870.72803376583392.106605354
#Sta/Elev= 30
       0 2450.22     5.6 2445.25    13.9 2443.43    18.5 2441.16    30.2 2432.16
    49.6 2419.86    94.7 2397.26   122.2 2385.94   131.7 2379.95   138.4 2374.31
   154.1 2365.61   165.7 2364.32   207.5 2363.61   216.7 2365.21  230.62 2360.64
   243.2 2359.83  258.512360.639   266.9 2362.66     279 2362.97   304.7 2365.84
   314.3 2368.94   328.7 2378.58   338.3 2382.32   352.7 2392.61   371.1 2403.86
   381.4 2412.33   395.8 2416.91   400.6 2422.72   405.7 2426.45   483.4 2474.03
#Mann= 3 ,-1,0
       0      .1       0  230.62    .045       0  258.51      .1       0
Bank Sta=230.62,258.51
XS Rating Curve= 0 ,0
Exp/Cntr(USF)=0,0
Exp/Cntr=0.3,0.1

Type RM Length L Ch R = 1 ,2092    ,318.6,339.9,349.3
XS GIS Cut Line= 4
2234979.45072739583925.6536971062235039.63425887 583747.13126321
2235050.14560005583678.7213043532235091.85756966583531.949653982
#Sta/Elev= 30
       0    2451    16.7 2439.34    51.2  2419.7    72.3 2406.25    93.4 2395.01
   131.4 2372.97   148.2 2361.81   160.9 2356.98   169.3 2355.74     182 2355.07
   190.4 2356.82   197.6 2352.48     214 2352.49   218.7  2353.5   238.9 2351.57
     247 2353.61   255.1 2354.22   263.4 2356.36   271.7 2357.31   288.3 2364.11
   296.6 2369.48   325.7 2392.11   334.1 2398.08   344.7 2404.53   354.9 2412.58
     359 2414.35   371.5 2416.26   375.6 2419.56   380.3 2424.31   410.2 2440.22
#Mann= 3 ,-1,0
       0      .1       0   197.6    .045       0     214      .1       0
#XS Ineff= 2 , 0
                          251.45         2358.54
Permanent Ineff=
       F       F
Bank Sta=197.6,214
XS Rating Curve= 0 ,0
Exp/Cntr(USF)=0,0
Exp/Cntr=0.3,0.1

Type RM Length L Ch R = 1 ,1752    ,88.9,85,96
XS GIS Cut Line= 6
2235173.96799575584013.3042277642235238.65675625583832.242193515
 2235304.3671328583847.5576548292235403.05074789583836.713301523
2235460.84713459583844.3043488372235518.88034615583666.655996463
#Sta/Elev= 30
       0 2439.44    17.1 2427.23    26.9 2423.03    63.8 2399.51    89.5 2384.61
   111.4 2369.78   127.6 2357.32   136.4 2352.71     170 2349.92   186.5 2352.81
   210.7 2351.12   227.4 2349.61   267.8 2342.55   283.8 2341.92   295.12342.559
   324.2 2343.91   344.4 2346.87   400.9 2345.13   417.7 2345.74   420.9  2346.8
   428.4 2350.79   441.8 2361.55     445 2363.15   471.4 2369.32   475.7 2372.48
   484.1 2381.07   554.8 2423.43   585.1 2439.55   597.2  2447.1   604.5 2453.09
#Mann= 3 ,-1,0
       0      .1       0   267.8    .045       0   295.1      .1       0
Bank Sta=267.8,295.1
XS Rating Curve= 0 ,0
Exp/Cntr(USF)=0,0
Exp/Cntr=0.3,0.1

Type RM Length L Ch R = 1 ,1667    ,364.6,356.1,329
XS GIS Cut Line= 6
2235199.05884425584073.0820816072235263.74760475583892.020047358
 2235329.4579813583907.3355086722235428.14159639583896.491155366
2235485.93798309 583904.082202682235543.97119465583726.433850306
#Sta/Elev= 30
       0 2458.63    21.1 2446.28    32.1 2437.73    42.4 2435.65    84.8 2409.81
    91.6 2407.13   131.6 2385.62   140.1 2382.47   161.3 2370.81   182.5 2355.23
   192.3 2350.74   223.5 2351.54   242.5 2348.94   254.6 2349.38   286.7 2344.23
   312.6 2341.51   323.1 2341.06   350.9 2341.52   359.4 2343.16   383.6 2343.48
     399 2341.71   420.7  2341.3   462.8 2343.13   475.4 2347.95     488 2357.46
   502.2 2360.56   530.1  2380.4   572.2 2403.86   589.8 2415.49   604.5 2423.57
#Mann= 3 ,-1,0
       0      .1       0   312.6    .045       0   350.9      .1       0
#XS Ineff= 2 , 0
                          438.09         2346.87
Permanent Ineff=
       F       F
Bank Sta=312.6,350.9
XS Rating Curve= 0 ,0
Exp/Cntr(USF)=0,0
Exp/Cntr=0.3,0.1

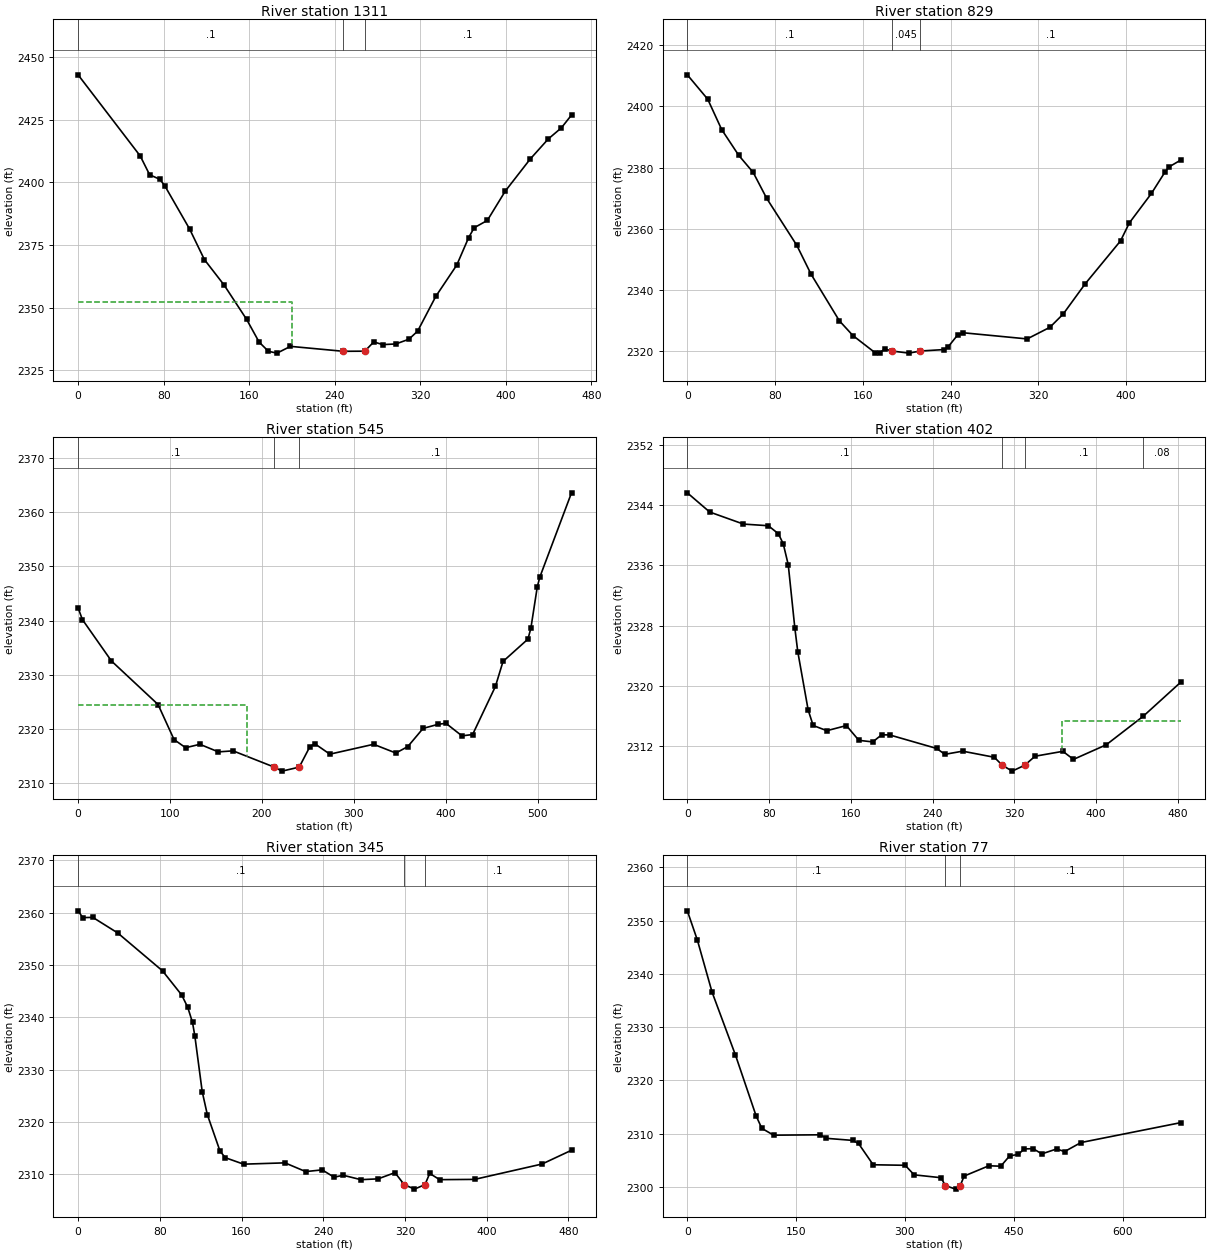
Type RM Length L Ch R = 1 ,1311    ,477.5,482.4,475.7
XS GIS Cut Line= 4
2235607.09228127584199.4504683572235709.60283043584022.089111257
2235740.43345424583957.3573888982235775.51309736583775.913529987
#Sta/Elev= 30
       0 2442.86    58.1 2410.48    66.9 2402.98    76.5 2401.15    81.2 2398.48
   104.3 2381.31   118.1 2369.13   136.6 2358.93   157.6 2345.25   169.3 2336.18
     178 2332.51     186 2331.79   198.6 2334.49     248 2332.52  268.08 2332.57
   276.5 2336.26   284.9 2335.19   297.1 2335.45   309.3 2337.33   317.5 2340.56
   334.5 2354.44   354.1 2366.93   365.2 2377.89   370.4 2381.84   382.7 2384.75
   399.4 2396.41   422.7 2409.21   439.7 2417.28   451.9 2421.69   461.4 2426.81
#Mann= 3 ,-1,0
       0      .1       0     248    .045       0  268.08      .1       0
#XS Ineff= 2 , 0
          199.64  2352.1
Permanent Ineff=
       F       F
Bank Sta=248,268.08
XS Rating Curve= 0 ,0
Exp/Cntr(USF)=0,0
Exp/Cntr=0.3,0.1

Type RM Length L Ch R = 1 ,829     ,280.1,283.4,286.8
XS GIS Cut Line= 4
2235902.21369581584313.2093824092236055.43090501 584272.58318578
2236109.84574219584157.7074184052236129.42125561583994.658998243
#Sta/Elev= 30
       0 2410.36    18.6 2402.38    31.3 2392.46    46.9 2383.99      60 2378.44
    72.4  2369.9    99.8 2354.55   112.8  2345.1   138.6 2329.85     151 2325.01
   171.1 2319.42   175.6 2319.42     180 2320.64  186.562319.958   202.1 2319.27
  212.082319.949   233.7 2320.43   237.5 2321.21   246.4  2325.2   251.7 2325.93
   309.8 2323.92   330.5 2327.72   342.6 2332.04   362.7 2341.96   394.9    2356
     403 2361.92   423.1 2371.55   435.7 2378.69   439.2 2380.24   449.8 2382.46
#Mann= 3 ,-1,0
       0      .1       0  186.56    .045       0  212.08      .1       0
Bank Sta=186.56,212.08
XS Rating Curve= 0 ,0
Exp/Cntr(USF)=0,0
Exp/Cntr=0.3,0.1

Type RM Length L Ch R = 1 ,545     ,142.9,143.4,149
XS GIS Cut Line= 4
2236092.00653734584404.2778233182236284.77808357584418.151533084
2236332.24077487584361.9264987692236402.33951896584101.246794215
#Sta/Elev= 30
       0 2342.35     4.7 2340.19    36.3 2332.55      87 2324.52   104.4 2318.05
     117 2316.55   132.5 2317.18   152.6 2315.78   168.6 2315.97   213.4 2312.97
   221.9 2312.23  240.59 2312.97   252.1 2316.72   257.4  2317.3   273.9 2315.36
   321.5 2317.18   345.7 2315.57   358.7 2316.76   375.3 2320.11   391.9 2320.88
   400.2 2321.05   417.6 2318.74   429.2 2318.98     454 2327.85   462.3 2332.47
   489.4 2336.59   492.6 2338.61   499.6 2346.27   502.4 2348.06   536.8 2363.58
#Mann= 3 ,0,0
       0      .1       0   213.4    .045       0  240.59      .1       0
#XS Ineff= 2 , 0
          184.22  2324.5
Permanent Ineff=
       F       F
Bank Sta=213.4,240.59
XS Rating Curve= 0 ,0
Exp/Cntr(USF)=0,0
Exp/Cntr=0.3,0.1

Type RM Length L Ch R = 1 ,402     ,56.7,56.6,56.4
XS GIS Cut Line= 6
2236159.15433788584530.6348725912236286.45860468584447.604429583
2236379.67938299584472.8930449762236486.78410701584421.324103782
2236508.10588077584406.9443028732236515.69470193 584320.55961564
#Sta/Elev= 30
       0 2345.64    21.9 2343.09    54.9 2341.49    79.3 2341.27    89.1 2340.21
    93.9 2338.87    98.8 2336.09   105.2 2327.74   108.1 2324.56   118.3 2316.79
   123.2 2314.74   136.6 2314.05   155.7 2314.73   167.9 2312.77   181.5 2312.56
   190.2  2313.5     198 2313.49   244.1 2311.69   252.1 2310.91   269.5 2311.33
   300.5 2310.52  308.282309.465     318 2308.68  330.272309.465   340.4 2310.66
   367.6 2311.31     378 2310.24   410.1 2312.18   446.3 2315.97     483 2320.49
#Mann= 4 ,-1,0
       0      .1       0  308.28    .045       0  330.27      .1       0
   446.3     .08       0
#XS Ineff= 2 , 0
                          367.03          2315.4
Permanent Ineff=
       F       F
Bank Sta=308.28,330.27
XS Rating Curve= 0 ,0
Exp/Cntr(USF)=0,0
Exp/Cntr=0.3,0.1

Type RM Length L Ch R = 1 ,345     ,268.7,268.4,264.9
XS GIS Cut Line= 6
 2236180.3742906584582.5876668562236307.67855739584499.557223847
 2236400.8993357 584524.845839242236508.00405972584473.276898047
2236529.32583348584458.8970971372236536.91465464584372.512409905
#Sta/Elev= 30
       0 2360.38     4.6 2359.08    14.4 2359.13    38.8 2356.15    82.7  2348.9
   101.4  2344.3   107.3 2341.96     112 2339.06   114.3 2336.46   121.5 2325.83
   126.5 2321.44   138.9 2314.48   144.1 2313.21     162 2311.97   202.5 2312.22
   222.8 2310.55   238.9 2310.88   250.6 2309.48   259.5 2309.85   276.8 2309.01
   293.6 2309.16   310.2 2310.35  319.182308.068   329.3  2307.2  339.572308.067
   344.2  2310.2   353.9 2309.01   388.1 2309.06   454.2    2312     483 2314.63
#Mann= 3 ,-1,0
       0      .1       0  319.18    .045       0  339.57      .1       0
Bank Sta=319.18,339.57
XS Rating Curve= 0 ,0
Exp/Cntr(USF)=0,0
Exp/Cntr=0.3,0.1

Type RM Length L Ch R = 1 ,77      ,,,
XS GIS Cut Line= 4
2236262.39889412584648.329721318 2236604.8388718584695.768774572
2236636.72231622584669.9257419292236588.46419096584380.445695943
#Sta/Elev= 30
       0 2351.82    13.9 2346.31    34.1 2336.57    66.4 2324.75    94.8 2313.37
   102.7 2311.02   118.9 2309.74   183.5 2309.81   191.6 2309.15   227.9 2308.76
     236 2308.18   256.2 2304.19   300.3 2304.09   312.7  2302.3   349.8 2301.76
   355.6 2300.29   369.8 2299.62  376.252300.285   381.6 2302.07   415.7    2304
   432.1 2303.92   444.3 2305.85   456.4 2306.14   464.3 2307.16   476.7 2307.21
   488.7 2306.23   509.2 2307.16     520 2306.66   542.7 2308.36   680.2 2312.09
#Mann= 3 ,-1,0
       0      .1       0   355.6    .045       0  376.25      .1       0
Bank Sta=355.6,376.25
XS Rating Curve= 0 ,0
Exp/Cntr(USF)=0,0
Exp/Cntr=0.3,0.1
LCMann Table=0

Chan Stop Cuts=-1
Use User Specified Reach Order=0
Composite Channel Slope=5